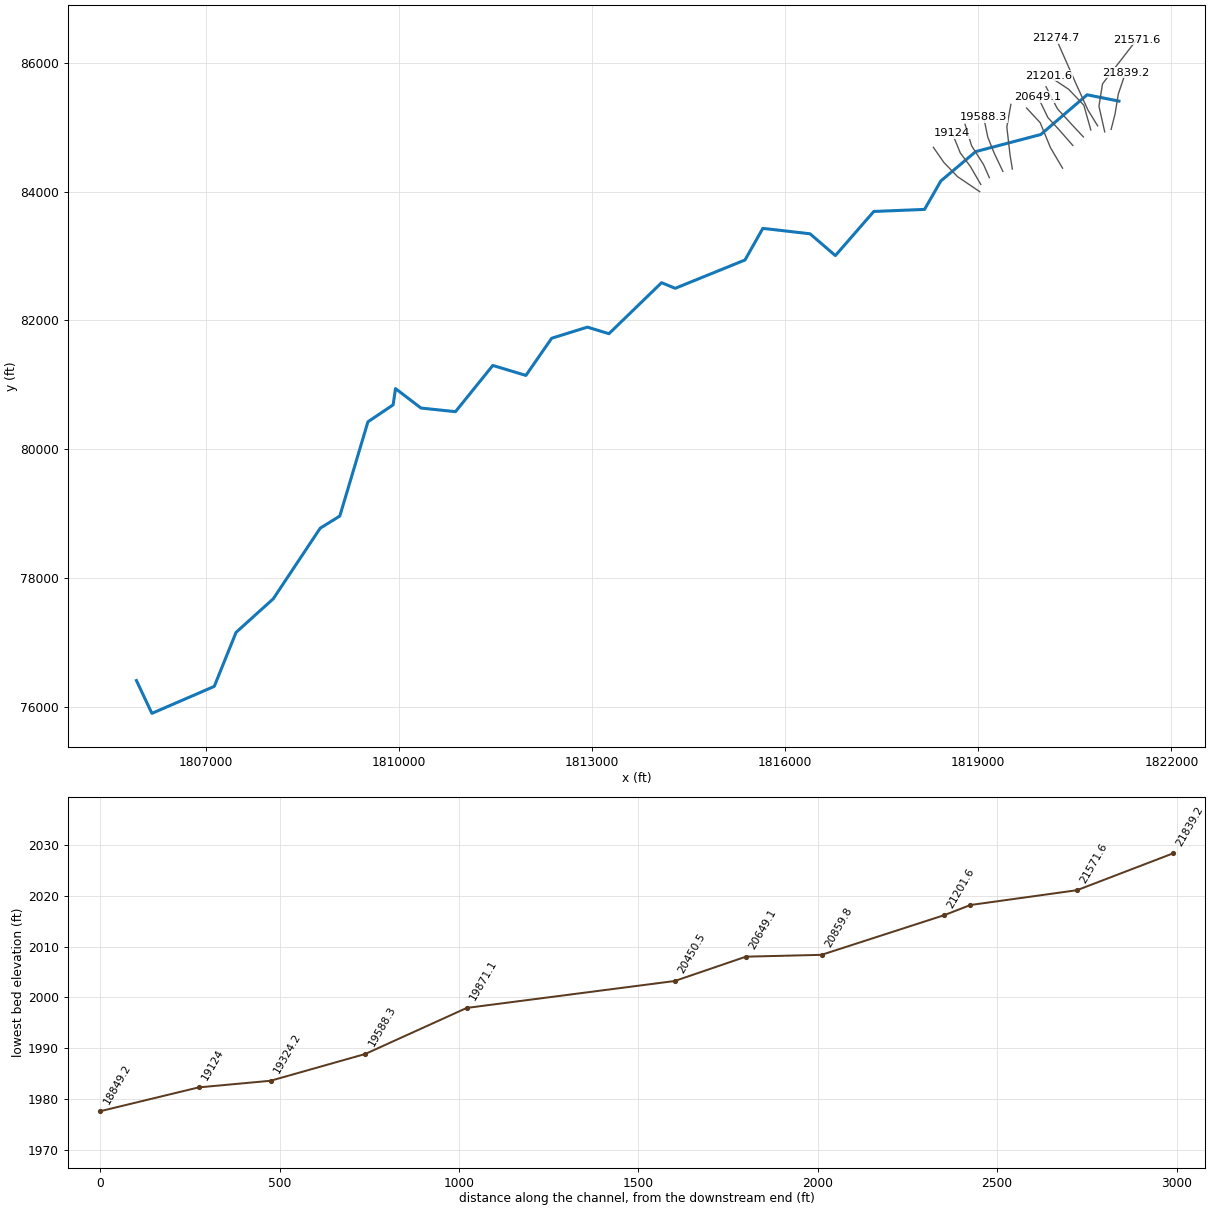
--- Horsepen Creek.prj (project) ---

Proj Title=Horsepen Creek
Current Plan=p01
Default Exp/Contr=0,0
English Units
Geom File=g01
Flow File=f01
Plan File=p01
BEGIN DESCRIPTION:
END DESCRIPTION:
DSS Export Rating Curves= 0
DSS Export Rating Curve Sorted= 0
DSS Export Volume Flow Curves= 0
DXF OffsetX= 0
DXF OffsetY= 0
DXF ScaleX= 0
DXF ScaleY= 0

--- Horsepen Creek.p01 (plan) ---

Plan Title=Floodplain
Program Version=4.00
Geom File=g01
Flow File=f01
K Sum by GR=0
Std Step Tol=0.01
Critical Tol=0.01
Num of Std Step Trials=20
Max Error Tol=0.3
Flow Tol Ratio=0.001
Split Flow NTrial=30
Split Flow Tol=0.02
Split Flow Ratio=0.02
Log Output Level=0
Friction Slope Method=1
Unsteady Friction Slope Method=2
Unsteady Bridges Friction Slope Method=1
Global Log Level=0
CheckData=False
Run HTab=0
Run UNet=0
Run PostProcess=0
UNET Theta=0
UNET Theta Warmup=0
UNET ZTol=0
UNET ZSATol=0
UNET MxIter=0
UNET MaxInSteps=0
UNET DtIC=0
UNET DtMin=0
UNET MaxCRTS=0
UNET WFStab=0
UNET SFStab=0
UNET WFX=0
UNET SFX=0
UNET DSS MLevel=0
UNET DZMax Abort=0
UNET Convert EG Bridges=0
UNET Use Existing IB Tables=0
UNET Froude Limit=0
UNET Froude Power=0
Write IC File=0
Echo Input=False
Echo Output=False
Write Detailed=0

--- Horsepen Creek.f01 (steady flow) ---

Flow Title=NFF Regression Equation
Program Version=4.00
Number of Profiles=1
Profile Names=P100yr
River Rch & RM=Horsepen Creek,Main      ,21839.2
968.2714
River Rch & RM=Horsepen Creek,Main      ,21571.6
970.9130
River Rch & RM=Horsepen Creek,Main      ,21274.7
1343.523
Boundary for River Rch & Prof#=Horsepen Creek,Main      ,1
Up Type=0
Dn Type=3
Dn Slope=0.014494

--- Horsepen Creek.g01 (geometry) ---

Geom Title=USGS 10m DEM
Program Version=4.00

River Reach=Horsepen Creek  ,Main
Reach XY= 30
     1821185.592       85406.671     1820691.153       85505.272
     1819970.121       84888.114     1818959.705        84623.26
     1818417.768       84166.779     1818164.332       83725.022
     1817376.049       83692.991     1816778.798       83007.771
     1816385.338       83346.302     1815652.061       83430.537
     1815374.517       82939.166       1814290.8       82499.631
     1814078.053       82586.566     1813260.541       81794.432
      1812925.76       81896.487     1812370.673       81723.696
     1811970.386        81146.56     1811455.856       81301.431
      1810876.05       80583.393     1810339.762        80639.71
     1809944.265       80941.772     1809907.147       80689.627
     1809515.489       80425.962     1809078.693       78962.021
     1808773.862       78773.424      1808045.23        77677.55
     1807466.521       77155.396     1807127.972       76316.384
     1806158.809       75897.265     1805918.406       76407.582

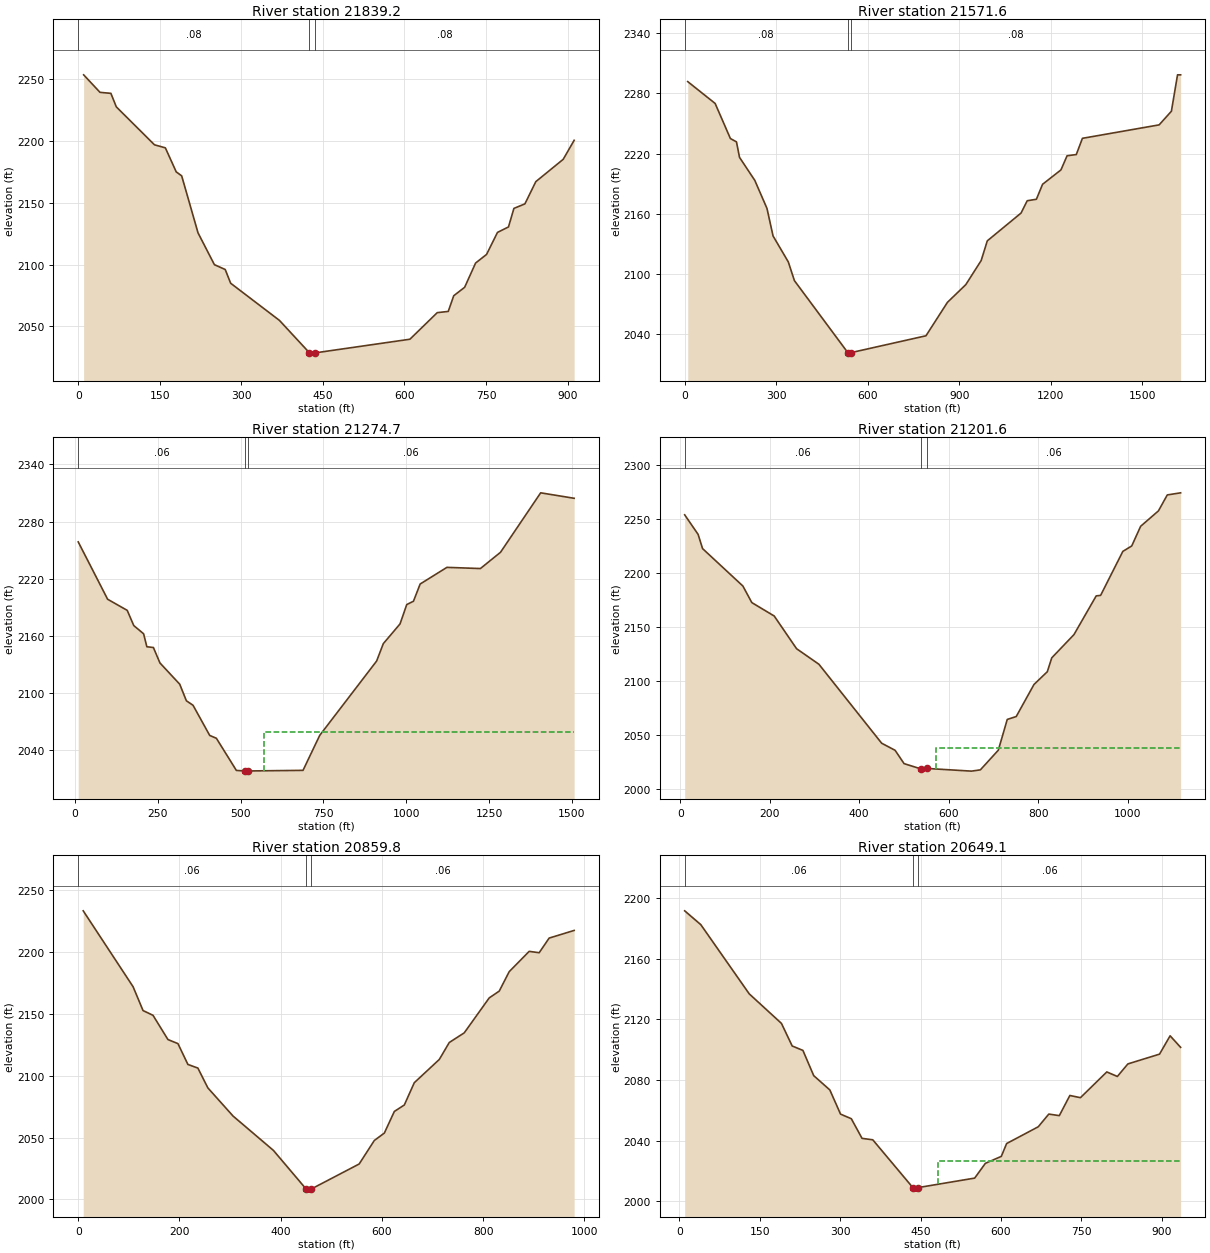
Type RM Length L Ch R = 1 ,21839.2 ,267.6,267.6,267.6
XS GIS Cut Line= 4
     1821063.933       84968.123     1821125.564       85210.874
     1821175.128       85516.158     1821287.865        85850.14
#Sta/Elev= 30
      10 2253.76    40.1 2239.57    60.1 2238.75    70.1  2227.8   140.3 2197.06
   160.3 2194.62   180.3 2175.13   190.3 2171.95   220.4 2125.73   250.5 2099.98
   270.4 2096.04   280.4 2084.94   370.2 2054.82     425 2028.71     430 2028.32
     435 2028.47   610.1 2039.58   660.4 2061.11   680.6  2062.1   690.7 2074.81
   710.8 2081.65   730.9 2101.29   751.1 2108.28   771.2 2126.12   791.4 2130.53
   801.4 2145.56   821.6 2149.21   841.7 2167.24   892.1 2185.33   912.2 2200.74
#Mann= 3 , 0 , 0
       0     .08       0     425    .045       0     435     .08       0
Bank Sta=425,435
XS Rating Curve= 0 ,0
Exp/Cntr=0.3,0.1

Type RM Length L Ch R = 1 ,21571.6 ,284.2,296.9,309.6
XS GIS Cut Line= 4
     1820964.328       84929.338     1820874.586       85329.018
     1820930.145       85675.682     1821459.992       86359.356
#Sta/Elev= 30
      10 2291.74    99.9 2269.96   149.9 2234.99   169.8 2231.68   179.8  2216.2
   229.8 2193.34   269.8 2165.32   289.7 2137.89   339.7    2112   359.7 2093.36
     535  2021.5     540 2021.08     545 2021.55   790.9 2038.36   861.3 2071.68
   921.6 2089.38   971.9 2113.38     992    2133  1102.7 2160.73  1122.8 2172.97
    1153 2174.48  1173.1 2189.36  1233.4 2203.71  1253.5  2217.8  1283.7 2219.02
  1303.8  2235.2  1555.3 2248.61  1595.5 2262.22  1615.6  2298.5  1625.7  2298.5
#Mann= 3 , 0 , 0
       0     .08       0     535    .045       0     545     .08       0
Bank Sta=535,545
XS Rating Curve= 0 ,0
Exp/Cntr=0.3,0.1

Type RM Length L Ch R = 1 ,21274.7 ,66.3,73.1,79.8
XS GIS Cut Line= 4
      1820854.02       85023.467     1820704.182        85267.32
     1820524.965       85661.011     1820206.589       86382.145
#Sta/Elev= 30
     9.9 2258.65    98.7 2198.48   157.9 2186.81   177.6 2170.87   207.3 2162.27
   217.1 2148.64   236.9 2147.84   256.6 2131.68   316.4 2109.35   336.5 2091.95
   356.6 2087.24   406.9 2055.61     427 2052.64   487.4  2018.9   512.6 2018.34
   517.6 2018.17   522.6 2018.34   688.6 2018.98     739 2055.68   910.8 2133.66
     931 2151.92   981.5 2172.62  1001.7 2192.89    1022 2196.39  1042.2 2214.46
    1123 2231.92  1224.1 2230.68  1284.7  2247.7    1406 2310.11  1507.1 2304.39
#Mann= 3 , 0 , 0
     9.9     .06       0   512.6    .045       0   522.6     .06       0
#XS Ineff= 2 , 0
                           570.3         2059.11
Permanent Ineff=
       F       F
Bank Sta=512.6,522.6
XS Rating Curve= 0 ,0
Exp/Cntr=0.3,0.1

Type RM Length L Ch R = 1 ,21201.6 ,342.3,341.8,341.4
XS GIS Cut Line= 4
     1820748.252       84958.832     1820639.546       85343.708
     1820404.507       85590.499     1820090.142       85799.096
#Sta/Elev= 30
      10 2254.08      40 2235.93      50 2222.71     140    2188     160 2172.61
     210 2160.16     260  2129.8   309.9 2115.37   450.1 2042.07   480.1 2035.51
   500.2 2023.13  537.25 2018.32   550.3 2018.68   650.5 2016.17   670.6 2017.33
   710.7  2035.6   730.7 2064.17   750.7 2066.83   790.4 2096.59   820.2 2108.46
   830.1 2121.32   879.7 2142.87   929.4 2178.82   939.3 2179.32   988.9 2220.13
  1008.8 2225.19  1028.7 2243.44  1068.4 2257.71  1088.2 2272.54    1118 2274.49
#Mann= 3 , 0 , 0
      10     .06       0  537.25    .045       0   550.3     .06       0
#XS Ineff= 2 , 0
                          572.32         2037.34
Permanent Ineff=
       F       F
Bank Sta=537.25,550.3
XS Rating Curve= 0 ,0
Exp/Cntr=0.3,0.1

Type RM Length L Ch R = 1 ,20859.8 ,210.4,210.7,210.9
XS GIS Cut Line= 4
     1820632.766       84851.053      1820457.69        85037.98
     1820229.379       85288.267     1820052.763       85630.104
#Sta/Elev= 30
     9.9 2233.25   108.4 2171.93   128.1 2152.65   147.8 2148.81   177.3 2129.22
     197 2125.96   216.7 2109.12   236.4  2106.2   256.1 2090.19   305.9 2067.42
   385.6 2039.67   450.4 2008.38   455.4 2008.37   460.4 2008.46     555 2028.68
   584.9 2047.65   604.8 2053.71   624.5 2071.14   644.2 2076.36   663.9 2094.36
   713.3 2113.15     733 2126.85   762.6 2134.66   811.9 2162.88   831.7 2168.37
   851.4 2184.09   890.9  2200.5   910.6  2199.4   930.3 2211.22   979.7 2217.41
#Mann= 3 , 0 , 0
       0     .06       0   450.4    .045       0   460.4     .06       0
Bank Sta=450.4,460.4
XS Rating Curve= 0 ,0
Exp/Cntr=0.3,0.1

Type RM Length L Ch R = 1 ,20649.1 ,206.2,198.7,191.1
XS GIS Cut Line= 4
     1820468.665       84718.538     1820263.562       84952.127
     1820081.249       85151.532     1819927.422        85470.58
#Sta/Elev= 30
      10 2191.53    40.1 2182.41   130.4 2136.79   190.5 2117.32   210.6  2102.4
   230.6 2099.48   250.7 2082.86   280.8 2073.42   300.8 2057.48   320.9 2054.43
   340.9 2041.48   360.9 2040.54   435.9 2008.92   440.9 2008.01   445.9 2009.05
     551 2015.28     571 2025.03   600.7 2029.61   610.6 2038.07   669.6 2049.12
   689.3 2057.49   708.9 2056.48   728.6 2069.77   748.3 2068.31   797.5 2085.29
   817.2  2082.3   836.8 2090.57   895.9 2097.03   915.6 2109.13   935.2 2101.51
#Mann= 3 , 0 , 0
      10     .06       0   435.9    .045       0   445.9     .06       0
#XS Ineff= 2 , 0
                          482.27         2026.45
Permanent Ineff=
       F       F
Bank Sta=435.9,445.9
XS Rating Curve= 0 ,0
Exp/Cntr=0.3,0.1

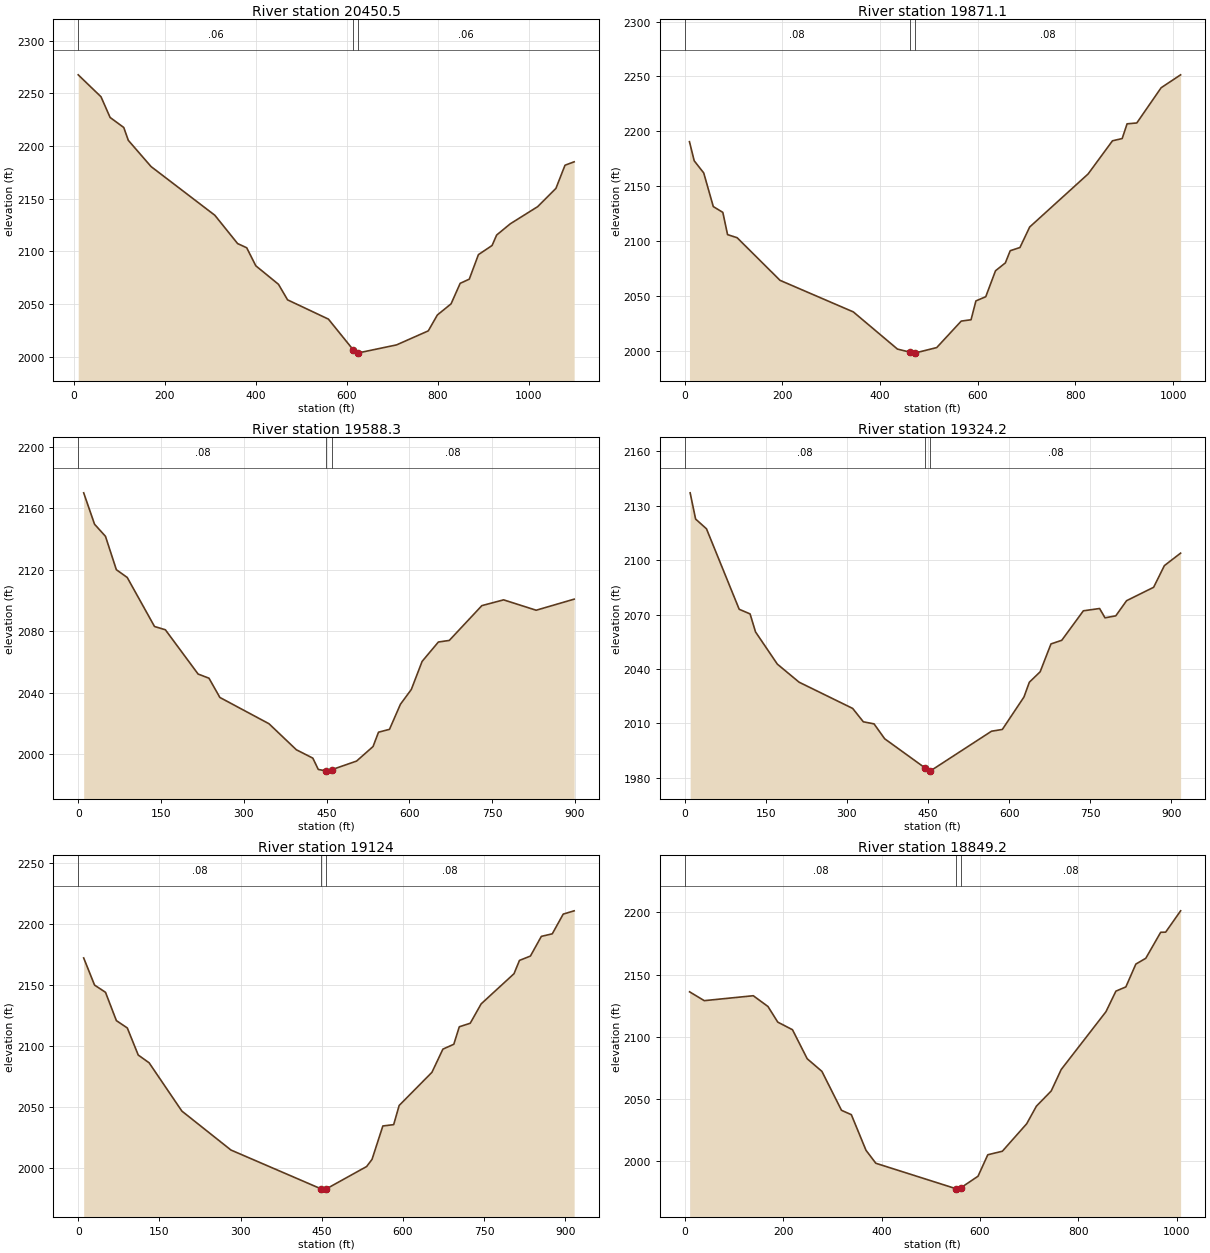
Type RM Length L Ch R = 1 ,20450.5 ,584.9,579.4,573.9
XS GIS Cut Line= 4
     1820309.141       84365.306      1820121.13       84684.354
     1819961.606        85071.77     1819750.361       85299.438
#Sta/Elev= 30
      10 2267.44    60.1  2246.6    80.1 2226.95   110.1 2217.45   120.1 2205.25
   170.1 2180.34   310.3  2134.1   360.3 2107.23   380.3 2103.25   400.3 2086.13
   450.1 2068.57   470.1  2053.8   559.9  2035.5   614.7 2006.19  619.35 2003.22
   624.7 2003.35   709.5 2011.02   779.3 2024.34   799.3 2039.45   829.4    2050
   849.4 2069.47   869.4 2073.44   889.5 2096.71   919.5 2105.41   929.6 2115.34
   959.6 2126.02  1019.7 2142.27  1059.8 2159.58  1079.8 2181.61  1099.9 2184.85
#Mann= 3 , 0 , 0
      10     .06       0   614.7    .045       0   624.7     .06       0
Bank Sta=614.7,624.7
XS Rating Curve= 0 ,0
Exp/Cntr=0.3,0.1

Type RM Length L Ch R = 1 ,19871.1 ,277.4,282.8,288.1
XS GIS Cut Line= 4
     1819528.724       84352.751     1819493.821       84564.611
     1819443.153       85003.402     1819505.823       85356.634
#Sta/Elev= 30
     9.8 2190.55    19.5 2173.18      39 2162.09    58.6 2131.44    78.1 2126.16
    87.8  2105.9   107.4 2103.07   195.2 2064.24   345.2 2035.49   435.6  2001.6
   460.7 1998.87   465.7 1997.93   470.7 1997.94   515.9 2002.98   566.1 2027.11
   586.2 2028.33   596.2 2045.51   616.3 2049.32   636.3 2072.98   656.4 2080.11
   666.4 2091.24   686.3 2094.14   706.2 2112.81   825.8 2161.14   875.7 2191.37
   895.6 2193.43   905.6 2206.84   925.5 2207.62   975.3  2239.7  1015.2 2251.48
#Mann= 3 , 0 , 0
       0     .08       0   460.7    .045       0   470.7     .08       0
Bank Sta=460.7,470.7
XS Rating Curve= 0 ,0
Exp/Cntr=0.3,0.1

Type RM Length L Ch R = 1 ,19588.3 ,260.4,264.1,267.8
XS GIS Cut Line= 4
     1819381.915       84315.579      1819245.98       84600.711
     1819146.516       84849.372     1819083.522       85157.712
#Sta/Elev= 30
     9.9 2169.88    29.6 2149.46    49.4 2141.58    69.1 2119.88    88.8 2114.82
   138.2 2082.95   157.9  2080.8   217.2 2052.01   236.9 2049.31   256.6 2036.79
   345.6 2019.69   395.2 2002.76     425 1997.33   434.9 1989.96   449.7 1988.97
   454.7 1988.87   459.7 1989.85   504.3 1995.42   534.1 2004.87     544 2014.19
   563.9 2016.06   583.7 2032.36   603.4 2041.96     623 2060.25   652.5 2072.86
   672.2 2073.87   731.2 2096.51   770.6 2100.27   829.6 2093.52   898.4 2100.72
#Mann= 3 , 0 , 0
       0     .08       0   449.7    .045       0   459.7     .08       0
Bank Sta=449.7,459.7
XS Rating Curve= 0 ,0
Exp/Cntr=0.3,0.1

Type RM Length L Ch R = 1 ,19324.2 ,198.7,200.2,201.7
XS GIS Cut Line= 4
     1819171.284       84218.347     1819081.399       84421.026
     1818896.214       84712.841     1818793.701       85047.037
#Sta/Elev= 30
    10.1 2137.18    20.2 2122.71    40.3 2117.33   100.8 2072.92   120.9 2070.36
     131 2060.42   171.3 2042.65   211.6 2032.67   310.6  2018.2   330.3 2010.82
   350.1 2009.68   369.8 2001.45   443.8  1985.5   448.8  1983.6   453.8 1983.62
   567.3 2005.63   587.3  2006.6   627.3 2024.52   637.2 2032.65   657.2 2038.41
   677.2 2053.79   697.2 2055.81   737.1 2072.07   767.1 2073.34   777.1  2068.2
     797 2069.29     817 2077.66     867 2085.05   886.9 2097.02   916.9  2103.9
#Mann= 3 , 0 , 0
       0     .08       0   443.8    .045       0   453.8     .08       0
Bank Sta=443.8,453.8
XS Rating Curve= 0 ,0
Exp/Cntr=0.3,0.1

Type RM Length L Ch R = 1 ,19124   ,272.4,274.7,277.1
XS GIS Cut Line= 4
     1819038.342       84112.691     1818876.753         84391.8
     1818721.039       84600.397     1818594.706       84908.886
#Sta/Elev= 30
    10.1 2172.18    30.2 2149.88    50.4 2143.96    70.5 2120.71    90.7 2114.66
   110.9 2092.43     131 2086.05   191.5 2046.41   282.2  2014.4   447.7  1982.7
   452.7  1982.3   457.7 1982.34   532.8 2000.86   542.8 2006.74   562.8 2034.17
   582.8 2035.27   592.9 2050.99   653.5 2078.25   673.7 2097.26   693.9 2101.29
     704 2115.63   724.2 2118.54   744.4 2134.45   805.1 2159.22   815.2 2170.15
   835.4 2173.72   855.6 2189.89   875.8 2191.99     896 2208.18   916.2 2210.87
#Mann= 3 , 0 , 0
       0     .08       0   447.7    .045       0   457.7     .08       0
Bank Sta=447.7,457.7
XS Rating Curve= 0 ,0
Exp/Cntr=0.3,0.1

Type RM Length L Ch R = 1 ,18849.2 ,18880,18849.2,18814.4
XS GIS Cut Line= 4
     1819021.554        84000.68     1818675.132       84235.187
      1818463.22       84456.463     1818301.976       84689.221
#Sta/Elev= 30
      10  2136.1    39.8 2129.01   139.4 2132.97   169.3 2124.31   189.2 2111.76
   219.1 2105.66     249 2082.35   278.9 2072.21   318.7 2040.94   338.7 2037.43
   368.5 2008.81   388.5 1998.39   551.7 1977.91   556.7 1977.61   561.7  1978.8
   596.2 1987.98     616 2005.21   645.6 2008.04   695.1 2030.13   714.8 2044.25
   744.9 2056.45   765.2 2073.69   856.2 2120.15   876.4 2136.66   896.6 2140.04
   916.9 2158.38   937.1 2163.04   967.4 2183.93   977.5 2184.04  1007.9 2201.17
#Mann= 3 , 0 , 0
       0     .08       0   551.7    .045       0   561.7     .08       0
Bank Sta=551.7,561.7
XS Rating Curve= 0 ,0
Exp/Cntr=0.3,0.1
Stream Node=Horsepen Creek  ,Main            , 0 , 0 ,Upstream end
Stream Node=Horsepen Creek  ,Main            , 0 , 1 ,Downstream end

Chan Stop Cuts=-1
Use User Specified Reach Order=0